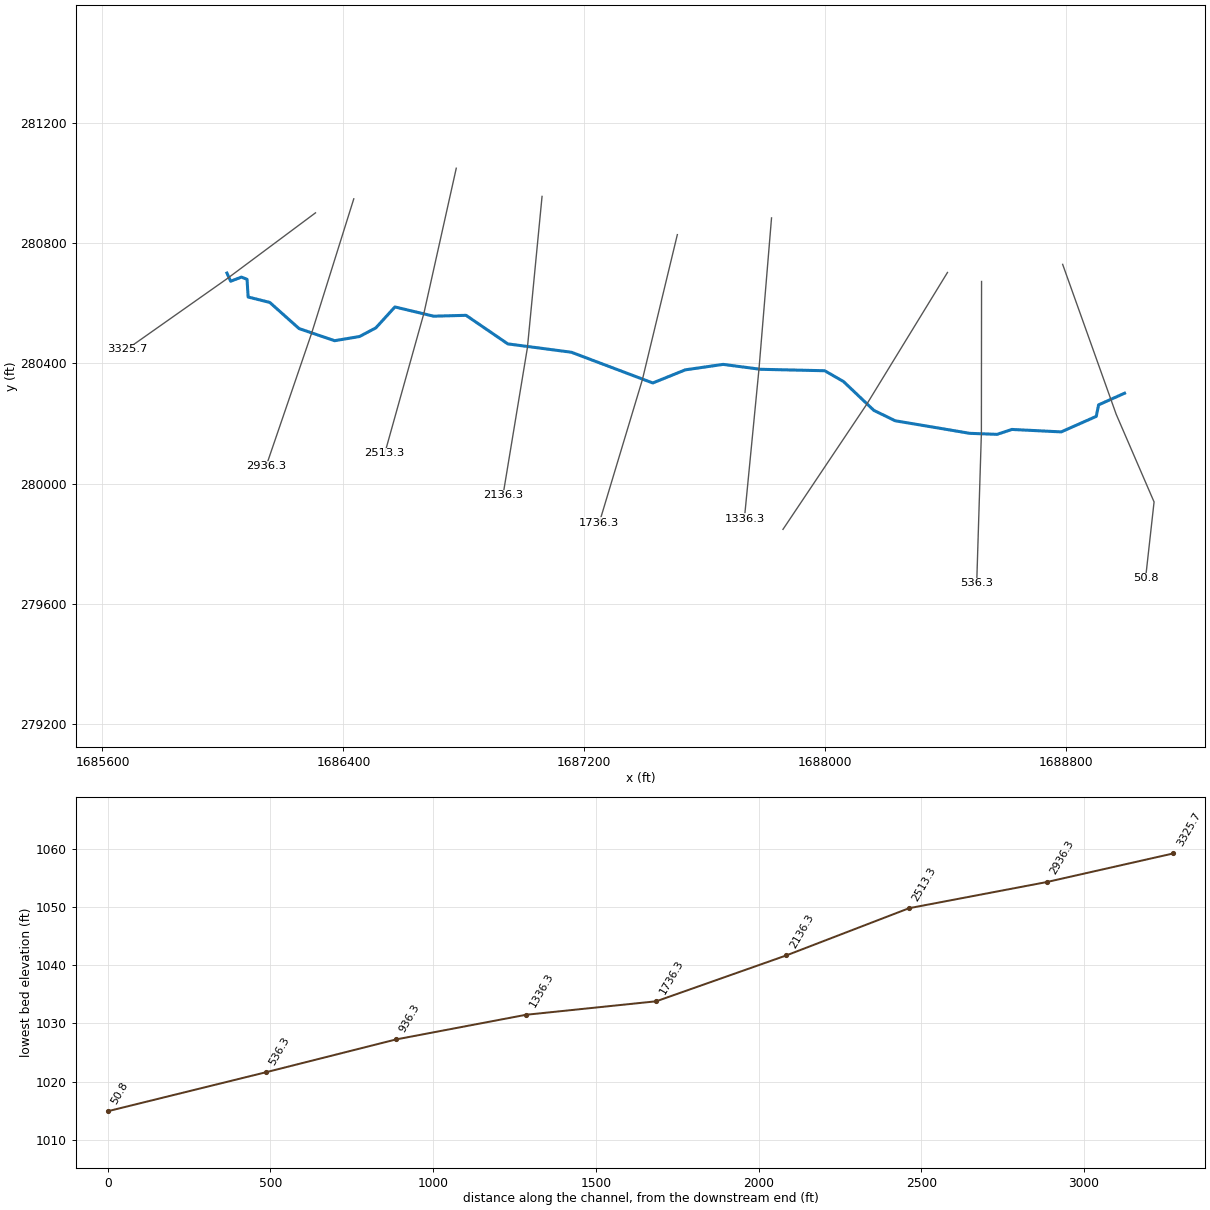
--- LickRn.prj (project) ---

Proj Title=LickRn
Current Plan=p01
Default Exp/Contr=0,0
English Units
Geom File=g01
Flow File=f01
Plan File=p01
BEGIN DESCRIPTION:
END DESCRIPTION:
DSS Export Rating Curves= 0
DSS Export Rating Curve Sorted= 0
DSS Export Volume Flow Curves= 0
DXF OffsetX= 0
DXF OffsetY= 0
DXF ScaleX= 0
DXF ScaleY= 0

--- LickRn.p01 (plan) ---

Plan Title=Floodplain
Program Version=4.00
Geom File=g01
Flow File=f01
K Sum by GR=0
Std Step Tol=0.01
Critical Tol=0.01
Num of Std Step Trials=20
Max Error Tol=0.3
Flow Tol Ratio=0.001
Split Flow NTrial=30
Split Flow Tol=0.02
Split Flow Ratio=0.02
Log Output Level=0
Friction Slope Method=1
Unsteady Friction Slope Method=2
Unsteady Bridges Friction Slope Method=1
Global Log Level=0
CheckData=False
Run HTab=0
Run UNet=0
Run PostProcess=0
UNET Theta=0
UNET Theta Warmup=0
UNET ZTol=0
UNET ZSATol=0
UNET MxIter=0
UNET MaxInSteps=0
UNET DtIC=0
UNET DtMin=0
UNET MaxCRTS=0
UNET WFStab=0
UNET SFStab=0
UNET WFX=0
UNET SFX=0
UNET DSS MLevel=0
UNET DZMax Abort=0
UNET Convert EG Bridges=0
UNET Use Existing IB Tables=0
UNET Froude Limit=0
UNET Froude Power=0
Write IC File=0
Echo Input=False
Echo Output=False
Write Detailed=0

--- LickRn.f01 (steady flow) ---

Flow Title=NFF Regression Equation
Program Version=4.00
Number of Profiles=1
Profile Names=P100yr
River Rch & RM=LickRn,Main      ,3325.7
726.2800
River Rch & RM=LickRn,Main      ,50.8
796.5905
Boundary for River Rch & Prof#=LickRn,Main      ,1
Up Type=0
Dn Type=3
Dn Slope=0.011145

--- LickRn.g01 (geometry) ---

Geom Title=USGS 3m DEM
Program Version=4.00

River Reach=LickRn          ,Main
Reach XY= 30
     1686013.196      280700.767     1686025.678      280673.646
     1686061.676      280687.328     1686080.156      280679.888
     1686083.758      280621.088     1686155.518      280603.087
     1686252.956      280515.966     1686371.038      280475.648
     1686453.598      280489.567     1686507.837      280518.366
     1686571.198      280587.966     1686699.839      280557.247
     1686807.357      280560.128     1686946.076      280465.086
     1687157.276      280437.247     1687427.518      280335.006
     1687535.518      280378.688     1687661.118       280396.84
     1687785.438      280380.518     1687998.557      280375.718
     1688060.956      280339.719     1688161.755      280243.719
     1688232.796       280209.16     1688480.478      280167.396
     1688570.716      280164.038     1688620.158       280180.36
     1688783.836      280172.198     1688900.286      280223.817
     1688908.046      280262.229     1688994.079      280300.838

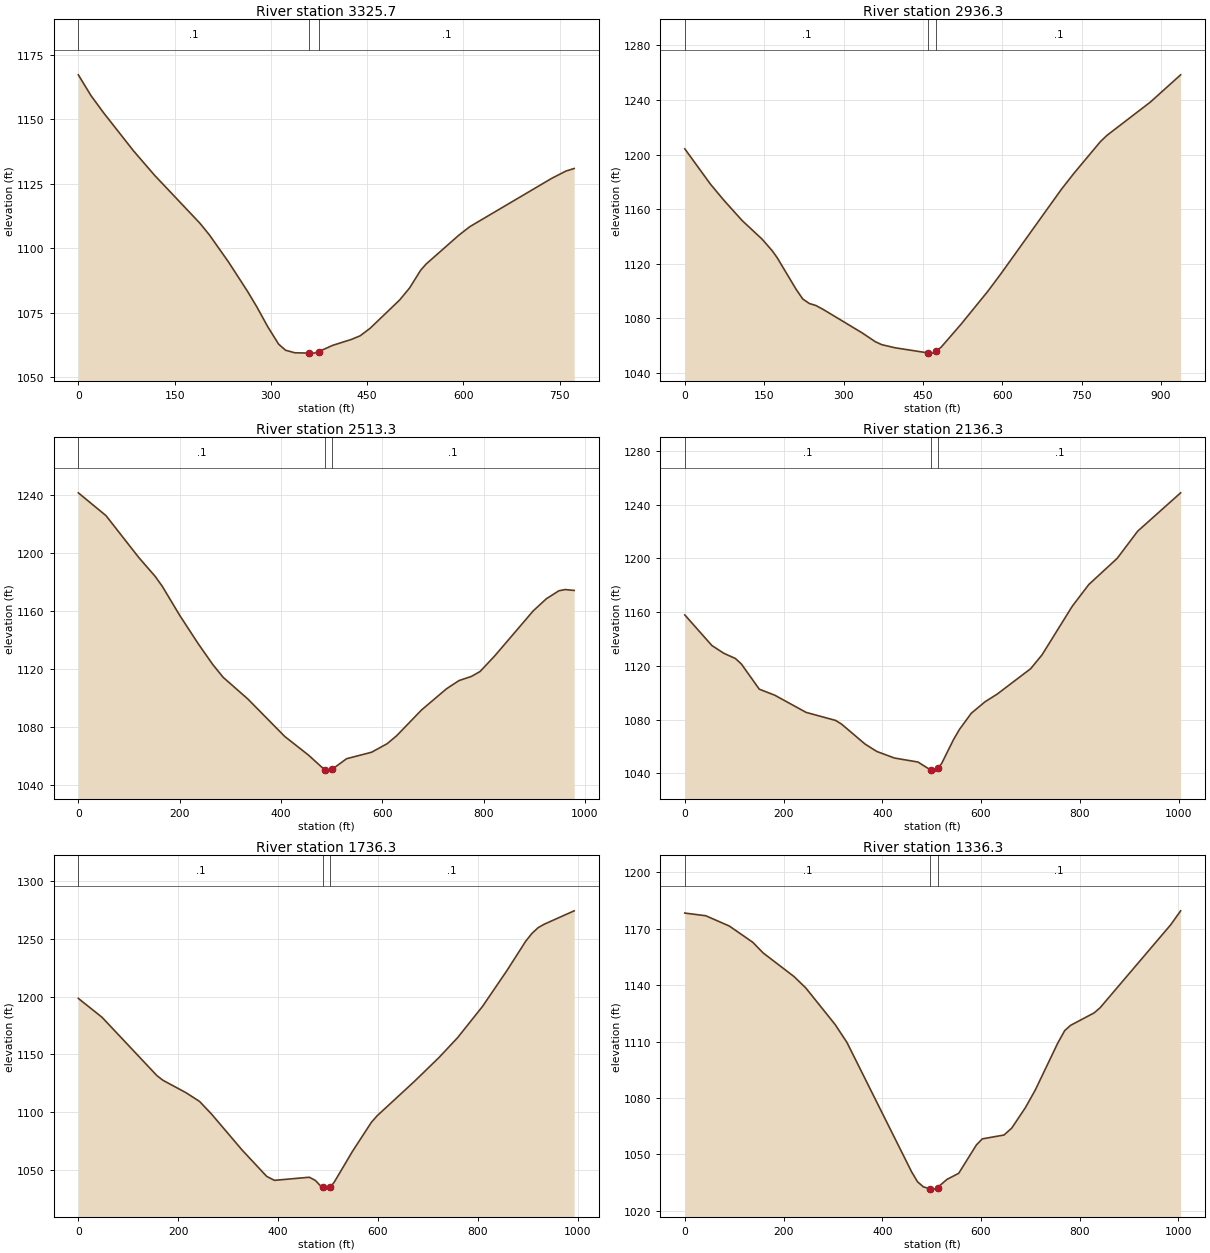
Type RM Length L Ch R = 1 ,3325.7  ,356.45,389.438,401.623
XS GIS Cut Line= 3
      1686307.42      280901.185     1686012.677       280681.17
     1685681.932      280447.743
#Sta/Elev= 30
       0 1167.14    19.7  1159.1    39.5 1152.38    85.9  1137.7   118.9 1128.18
   189.6 1109.58   204.5 1105.01   234.1 1094.57   263.7  1083.2   278.2 1077.18
   295.1 1069.54   312.1 1062.75     323 1060.38   337.3 1059.41   359.8 1059.28
   367.4 1059.27   374.8 1059.89   396.5  1062.3   425.6 1064.59   439.1 1065.99
   454.6 1068.88   500.8  1079.9   516.3 1084.57   533.4 1091.39   541.8 1093.77
     593    1105   610.1  1108.3   737.8 1127.04   759.8 1129.84   772.6 1130.83
#Mann= 3 , 0 , 0
       0      .1       0   359.8    .045       0   374.8      .1       0
Bank Sta=359.8,374.8
XS Rating Curve= 0 ,0
Exp/Cntr=0.3,0.1

Type RM Length L Ch R = 1 ,2936.3  ,421.611,423.012,423.845
XS GIS Cut Line= 3
      1686434.57      280947.774     1686294.913       280501.64
     1686143.235      280057.411
#Sta/Elev= 30
       0 1204.16    48.7 1178.14    73.6 1166.57   108.3 1151.59   146.2 1137.87
   165.1 1129.47   174.6 1124.31   210.4 1101.11   222.9 1094.05   235.3 1090.74
   247.8 1089.25   260.9 1086.52   334.9 1069.25   359.7 1062.78   372.2 1060.54
   397.1 1058.28     460 1054.47   467.5 1054.34   471.7  1054.6     475 1055.77
   484.3 1058.66   521.9  1075.5   572.1 1099.45   597.2 1112.46   711.4 1174.37
   735.2 1186.15   785.4 1209.48   797.9 1214.09   879.8 1238.47   936.9 1258.43
#Mann= 3 , 0 , 0
       0      .1       0     460    .045       0     475      .1       0
Bank Sta=460,475
XS Rating Curve= 0 ,0
Exp/Cntr=0.3,0.1

Type RM Length L Ch R = 1 ,2513.3  ,374.257,376.988,379.348
XS GIS Cut Line= 3
     1686774.922      281049.656     1686667.455      280566.943
     1686537.422      280100.603
#Sta/Elev= 30
       0 1241.23    54.7 1225.52   118.9 1196.93     152 1183.64   165.9 1176.84
   200.7 1156.64   237.2 1137.19   265.4 1123.15   285.8 1114.38   334.5 1099.48
   407.4  1073.7   454.4 1060.84   486.1  1050.8   492.6 1049.84   501.1 1051.13
   529.5 1058.38   578.8 1062.83   609.3 1068.64   628.1  1074.1   677.4 1091.88
   726.7 1106.47   751.4 1112.11     776 1114.99     793 1118.36   821.9 1129.07
   897.9 1160.05   923.9  1168.4   948.6 1173.87   960.9 1174.71   978.7  1174.1
#Mann= 3 , 0 , 0
       0      .1       0   486.1    .045       0   501.1      .1       0
Bank Sta=486.1,501.1
XS Rating Curve= 0 ,0
Exp/Cntr=0.3,0.1

Type RM Length L Ch R = 1 ,2136.3  ,403.222,400,397.037
XS GIS Cut Line= 3
     1687059.799      280955.894     1687011.192      280452.515
     1686929.979      279960.617
#Sta/Elev= 30
       0  1157.9    54.9 1135.14    78.7 1129.45   102.6 1125.46   114.5 1121.46
   150.9 1102.66   182.4 1098.16   245.7 1085.41   305.4 1079.43   317.3 1076.76
     365 1061.89   388.8 1056.37   424.6 1051.46   472.3 1048.49   498.2 1042.51
   508.1 1041.72   513.2 1044.05   520.2 1047.37   544.2 1065.09   556.3 1072.74
   580.3 1084.77   608.4 1093.38   632.5 1098.93   700.7 1117.95   723.7 1128.26
   784.9 1164.41   818.4 1180.54   875.8 1199.97   917.3 1220.17  1004.3 1248.71
#Mann= 3 , 0 , 0
       0      .1       0   498.2    .045       0   513.2      .1       0
Bank Sta=498.2,513.2
XS Rating Curve= 0 ,0
Exp/Cntr=0.3,0.1

Type RM Length L Ch R = 1 ,1736.3  ,395.98,400,404.948
XS GIS Cut Line= 3
     1687509.097      280828.683     1687392.813      280345.437
      1687250.09      279870.546
#Sta/Elev= 30
       0 1198.36    47.4 1182.11   157.3 1131.79   169.6 1127.69   215.6 1117.02
   242.8 1109.47   267.3 1098.31   328.3 1067.39   377.2 1044.82   392.7  1041.4
   462.6 1044.08   474.8 1041.28   487.1 1035.67   489.5 1035.36   499.3 1033.82
   504.5 1035.92   511.7  1039.3   548.9 1066.35   586.7 1091.38   598.5 1097.17
   672.9 1126.73   722.5 1147.47   759.6 1164.55   809.2 1191.34   858.8 1222.72
     896 1247.78   908.4 1254.43   920.8  1259.4   933.2 1262.42   992.9 1273.92
#Mann= 3 , 0 , 0
       0      .1       0   489.5    .045       0   504.5      .1       0
Bank Sta=489.5,504.5
XS Rating Curve= 0 ,0
Exp/Cntr=0.3,0.1

Type RM Length L Ch R = 1 ,1336.3  ,410.568,400,388.832
XS GIS Cut Line= 3
     1687821.868      280884.307     1687780.216      280381.678
     1687731.777      279883.968
#Sta/Elev= 30
       0  1178.4    42.5 1176.97    90.2  1171.5   137.8 1162.83   158.6 1157.21
   221.2 1144.63   245.1 1138.56   304.6 1119.07   328.5 1109.54   459.5 1040.69
   471.4 1035.43   483.3  1032.7   496.9 1031.68   507.2  1031.5   511.9 1032.36
     531 1036.66   554.9 1039.94   590.7 1055.01   602.6 1058.24   646.6 1060.29
   662.2 1063.95   690.1 1074.92   709.9  1084.2   755.3 1109.09   769.6 1115.86
   781.5 1118.65   829.2 1125.29   841.2 1127.99   984.3 1172.17  1004.4 1179.59
#Mann= 3 , 0 , 0
       0      .1       0   496.9    .045       0   511.9      .1       0
Bank Sta=496.9,511.9
XS Rating Curve= 0 ,0
Exp/Cntr=0.3,0.1

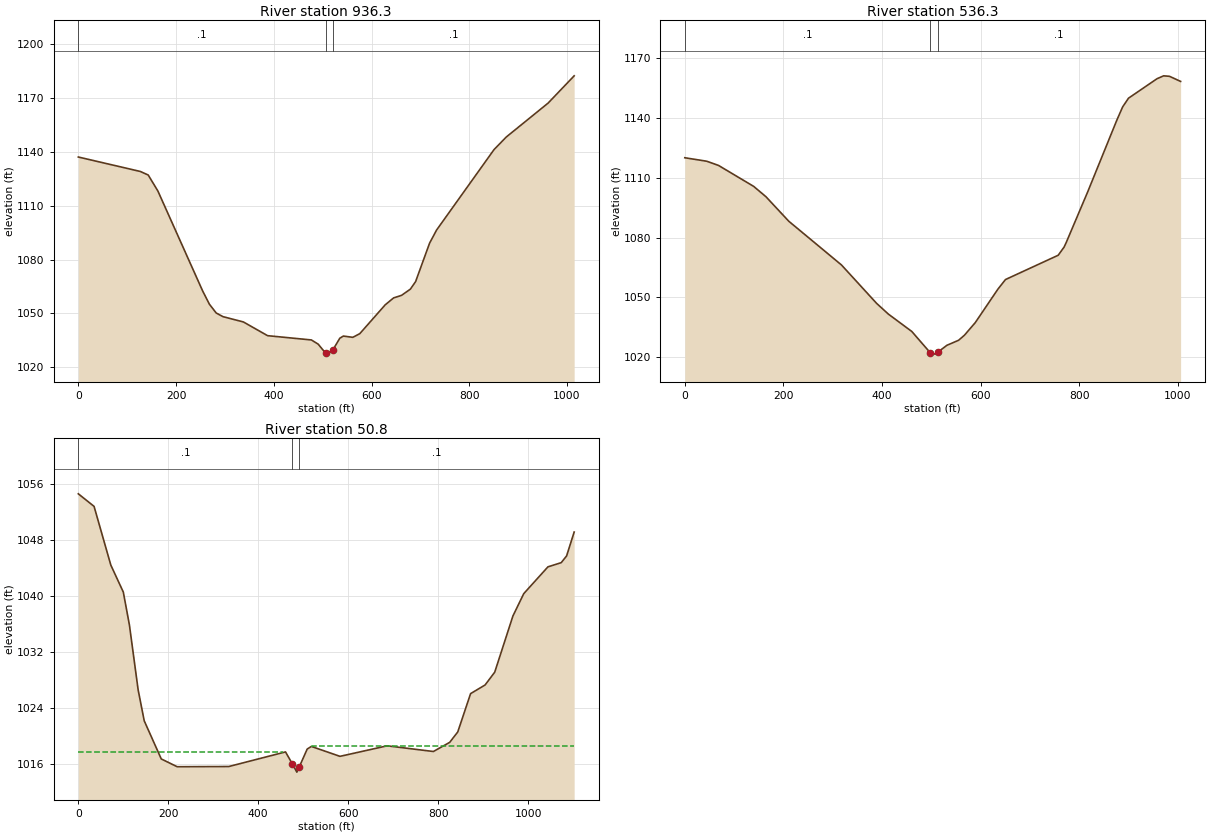
Type RM Length L Ch R = 1 ,936.3   ,387.649,400,412.605
XS GIS Cut Line= 3
     1688406.165      280702.729     1688138.229      280264.454
     1687859.886      279847.827
#Sta/Elev= 30
       0 1137.15   126.8  1129.1     143 1127.12   162.8 1118.21   254.3 1062.55
   268.2 1055.09   282.2 1050.18   296.1 1048.14   337.8 1045.19   387.3 1037.54
     477 1035.15   490.9  1032.8   506.2 1027.72   508.2 1027.25   521.2 1029.72
   535.1 1036.12   542.5 1037.32   561.7 1036.62     576 1038.66   628.1 1054.76
   645.2 1058.59   661.6 1060.04   679.5 1063.48   690.2 1067.68   718.8 1089.09
     733 1096.37   850.7 1141.28   875.8 1148.31   961.5 1167.24  1014.7 1182.42
#Mann= 3 , 0 , 0
       0      .1       0   506.2    .045       0   521.2      .1       0
Bank Sta=506.2,521.2
XS Rating Curve= 0 ,0
Exp/Cntr=0.3,0.1

Type RM Length L Ch R = 1 ,536.3   ,473.173,485.492,495.816
XS GIS Cut Line= 3
     1688519.337      280672.821      1688518.76      280167.398
     1688503.222      279667.723
#Sta/Elev= 30
       0    1120    44.6 1118.25    68.4 1116.15   139.6 1105.66   164.4 1100.51
   210.8  1088.2   317.7 1066.27   388.9 1047.04   412.7 1041.67   460.2 1032.96
   497.9 1022.24   507.6  1021.6   512.9 1022.55   531.4 1026.02   555.2 1028.55
     567 1031.08   588.9 1037.38   634.9 1054.18   650.2 1058.97   757.1 1071.15
     769 1075.22   773.2 1077.44   816.5 1102.67   875.9  1138.8   887.8  1145.5
   899.6 1149.84   957.5 1159.61   970.9 1161.05   982.8  1160.8  1005.3 1158.25
#Mann= 3 , 0 , 0
       0      .1       0   497.9    .045       0   512.9      .1       0
Bank Sta=497.9,512.9
XS Rating Curve= 0 ,0
Exp/Cntr=0.3,0.1

Type RM Length L Ch R = 1 ,50.8    ,46.579,50.819,55.574
XS GIS Cut Line= 4
     1688788.654      280729.757     1688966.463        280230.7
     1689092.227      279939.126     1689064.046      279685.501
#Sta/Elev= 30
       0 1054.57      35 1052.78    72.2 1044.42     100 1040.57   113.6 1035.87
     133 1026.63   146.5 1022.22   184.4 1016.78   219.8 1015.67   334.7  1015.7
   460.7 1017.78     476 1016.06   485.9  1014.9     491  1015.6   508.9 1018.19
   518.2 1018.56   581.8 1017.15   686.7 1018.65   789.5 1017.84   825.7 1019.14
   843.7 1020.63   872.2 1026.09   904.4 1027.32   925.9 1029.15   966.3 1037.15
   990.4 1040.34  1044.2 1044.16  1073.8 1044.76  1085.7 1045.72  1102.5 1049.12
#Mann= 3 , 0 , 0
       0      .1       0     476    .045       0     491      .1       0
#XS Ineff= 2 , 0
          455.98  1017.8  518.69         1018.57
Permanent Ineff=
       F       F
Bank Sta=476,491
XS Rating Curve= 0 ,0
Exp/Cntr=0.3,0.1

Chan Stop Cuts=-1
Use User Specified Reach Order=0